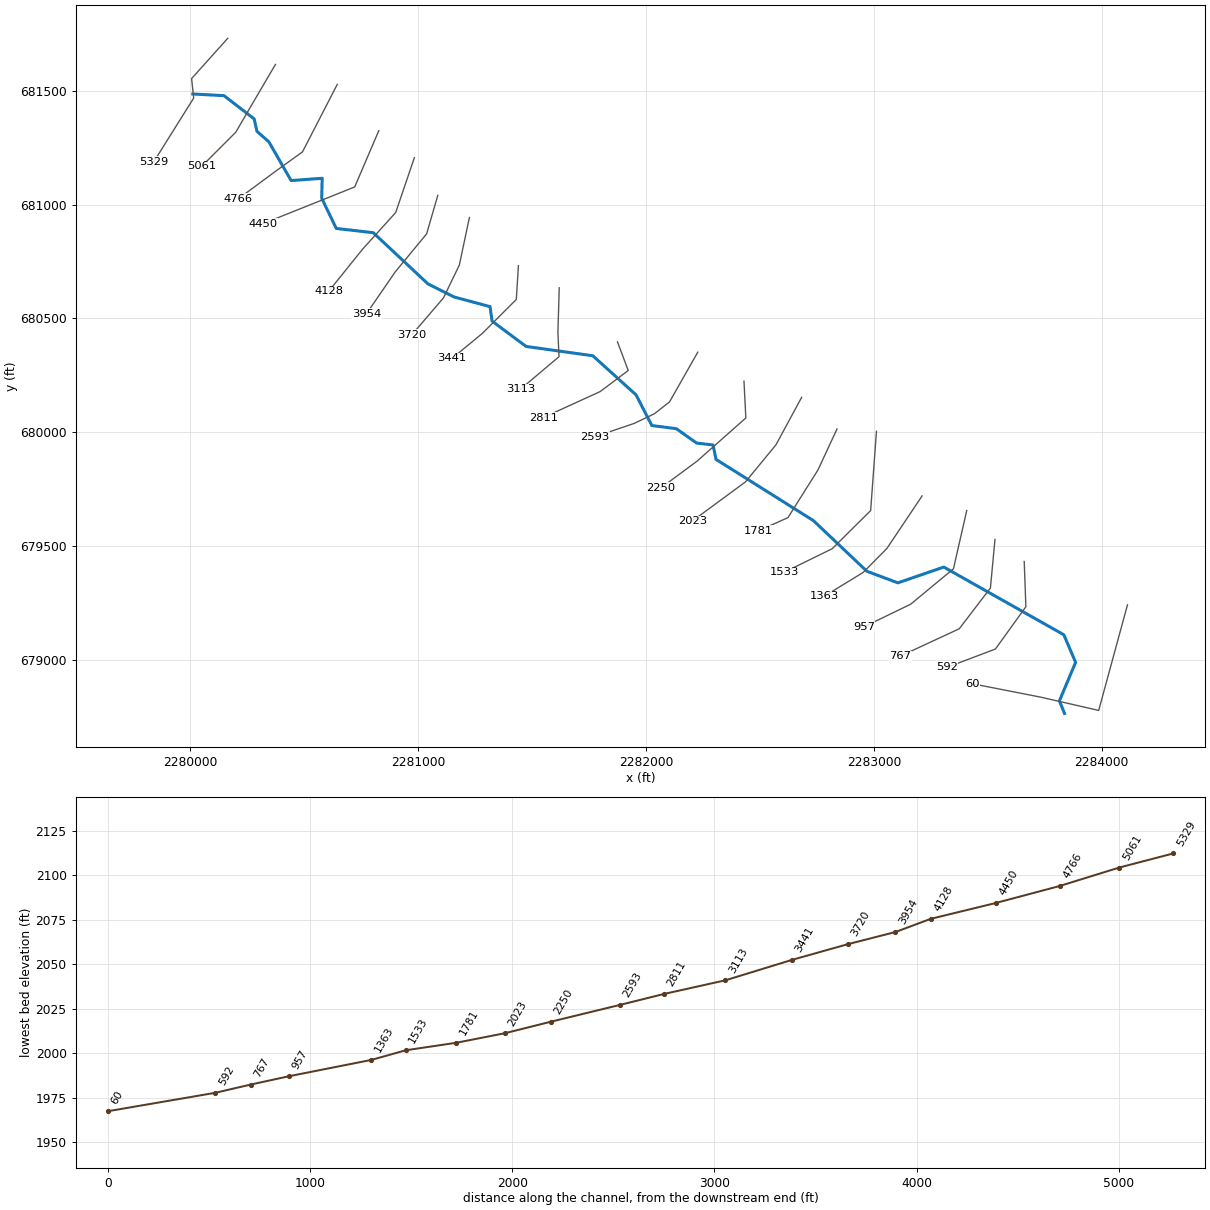
--- BEAVCK1T2.prj (project) ---

Proj Title=BEAVCK1T2
Current Plan=p01
Default Exp/Contr=0,0
English Units
Geom File=g01
Flow File=f01
Plan File=p01
BEGIN DESCRIPTION:
----------MODEL BY WOOD PLC 2022----------
AFH study
Randolph County, WV
HEC-RAS Version: RAS 6.2
Vertical Datum: NAVD88
Projection: NAD 1983 StatePlane West Virginia S FIPS 4702 (US Feet)
Terrain: 1-meter LIDAR (FEMA Region III 3DEP collected 2016-2018)
Land Use: 2019 NLCD
Hydrologic Method:
WV SIR2010-5033 regression equations
Additional Model Notes:
None
END DESCRIPTION:
DSS Export Rating Curves= 0
DSS Export Rating Curve Sorted= 0
DSS Export Volume Flow Curves= 0
DXF OffsetX= 0
DXF OffsetY= 0
DXF ScaleX= 0
DXF ScaleY= 0

--- BEAVCK1T2.p01 (plan) ---

Plan Title=Floodplain
Program Version=6.20
Short Identifier=Floodplain
Geom File=g01
Flow File=f01
Subcritical Flow
K Sum by GR= 0
Std Step Tol= 0.01
Critical Tol= 0.01
Num of Std Step Trials= 20
Max Error Tol= 0.3
Flow Tol Ratio= 0.001
Split Flow NTrial= 30
Split Flow Tol= 0.02
Split Flow Ratio= 0.02
Log Output Level= 0
Friction Slope Method= 1
Unsteady Friction Slope Method= 2
Unsteady Bridges Friction Slope Method= 1
Parabolic Critical Depth
Global Vel Dist= 0 , 0 , 0
Global Log Level= 0
CheckData=True
Encroach Param=-1 ,0,0, 0
Mapping Interval=1HOUR
Computation Time Step Use Courant=        0
Computation Time Step Use Time Series=    0
Computation Time Step Count To Double=0
Computation Time Step Max Doubling=0
Computation Time Step Max Halving=0
Computation Time Step Residence Courant=0
Run HTab= 0
Run UNet= 0
Run Sediment= 0
Run PostProcess= 0
Run WQNet= 0
Run RASMapper=-1
UNET Theta= 0
UNET Theta Warmup= 0
UNET ZTol= 0
UNET ZSATol= 0
UNET MxIter= 0
UNET Max Iter WO Improvement= 0
UNET MaxInSteps= 0
UNET DtIC= 0
UNET DtMin= 0
UNET MaxCRTS= 0
UNET WFStab= 0
UNET SFStab= 0
UNET WFX= 1
UNET SFX= 1
UNET Gravity=32.174
UNET 1D Methodology=Finite Difference
UNET DSS MLevel= 1
UNET Pardiso=0
UNET DZMax Abort= 0
UNET Use Existing IB Tables= 0
UNET Froude Reduction=False
UNET Froude Limit= 0
UNET Froude Power= 0
UNET D1 Cores= 0
UNET WindReference=Eulerian
UNET WindDragFormulation=Hsu (1988)
UNET D2 Coriolis=0
UNET D2 Cores= 0
UNET D2 Theta= 1
UNET D2 Theta Warmup= 1
UNET D2 Z Tol= 0.01
UNET D2 Volume Tol= 0.01
UNET D2 Max Iterations= 20
UNET D2 Equation= 0
UNET D2 RampUpFraction=0.1
UNET D2 TimeSlices= 1
UNET D2 Turbulence Formulation=Non-Conservative (original)
UNET D2 Eddy Viscosity=0.3
UNET D2 Transverse Eddy Viscosity=0.1
UNET D2 Smagorinsky Mixing=0
UNET D2 BCVolumeCheck=0
UNET D2 Cores=0
UNET D2 SolverType=PARDISO (Direct)
UNET D2 Minimum Iterations= 2147483647
UNET D2 Maximum Iterations= 2147483647
UNET D2 Restart Number= 10
UNET D2 Relaxation Coeff=1.3
UNET D2 SOR Precondition Iterations= 10
UNET D2 ILUT Maximum Fill= 8
UNET D2 ILUT Tolerance=1E-08
UNET D1D2 MaxIter= 0
UNET D1D2 ZTol=0.01
UNET D1D2 QTol=0.1
UNET D1D2 MinQTol=1
Write IC File= 0
Write IC File at Fixed DateTime=0
Write IC File at Sim End=0
Echo Input=False
Echo Parameters=False
Echo Output=False
Write Detailed= 0
HDF Write Warmup=0
HDF Write Time Slices=0
HDF Flush=0
HDF Compression= 1
HDF Chunk Size= 1
HDF Spatial Parts= 1
HDF Use Max Rows=0
HDF Fixed Rows= 1
Calibration Method= 0
Calibration Iterations= 20
Calibration Max Change=0.05
Calibration Tolerance=0.2
Calibration Maximum=1.5
Calibration Minimum=0.5
Calibration Optimization Method= 1
WQ AD Non Conservative
WQ ULTIMATE=-1
WQ Max Comp Step=1HOUR
WQ Output Interval=15MIN
WQ Output Selected Increments= 0
WQ Output face flow=0
WQ Output face velocity=0
WQ Output face area=0
WQ Output face dispersion=0
WQ Output cell volume=0
WQ Output cell surface area=0
WQ Output cell continuity=0
WQ Output cumulative cell continuity=0
WQ Output face conc=0
WQ Output face dconc_dx=0
WQ Output face courant=0
WQ Output face peclet=0
WQ Output face adv mass=0
WQ Output face disp mass=0
WQ Output cell mass=0
WQ Output cell source sink temp=0
WQ Output nsm pathways=0
WQ Output nsm derived pathways=0
WQ Create Restart=0
WQ Fixed Restart=0
WQ System Summary=0
WQ Write To DSS=0
Sorting and Armoring Iterations= 10
XS Update Threshold= 0.02
Bed Roughness Predictor= 0
Hydraulics Update Threshold= 0.02
Energy Slope Method= 1
Volume Change Method= 1
Sediment Retention Method= 0
Sediment TS Multiplier= 1
Warm Up Method= 0
XS Weighting Method= 0
Number of US Weighted Cross Sections= 1
Number of DS Weighted Cross Sections= 1
Upstream XS Weight=0
Main XS Weight=1
Downstream XS Weight=0
Number of DS XS's Weighted with US Boundary= 1
Upstream Boundary Weight= 1
Weight of XSs Associated with US Boundary= 0
Number of US XS's Weighted with DS Boundary= 1
Downstream Boundary Weight= 0.5
Weight of XSs Associated with DS Boundary= 0.5
Percentile Method= 0
Sediment Output Level= 3
Mass or Volume Output= 0
Output Increment Type= 1
Profile and TS Output Increment= 1
Transport Output Increment 1
XS Output Flag= 0
XS Output Increment= 10
Read HDF5 Sediment Hotstart= 0
Sediment Hotstart Type= 0
Write Gradation File= 0
Read Gradation Hotstart= 0
Write HDF5 File= 1
Write Binary Output= 1
Write DSS Sediment File= 0
DSS Sediment Output Type= 1
SV Curve= 0
Specific Gage Flag= 0
Subcell Erosion Methods= 0
Subcell Deposition Methods= 0
Advection Scheme= 1
Matrix Solver= 0
Implicit Weighting Factor= 1
Maximum Outer Loop Convergence Iterations= 5
Convergence Maximum Absolute= 0.001
Convergence RMSE= 0.0001
Grain Fractions Max Abs Error= 0.001
Max Subgrid Regions= 1
Max Subgrid Length Scale= 3.402823E+38
Initial Layer Thickness= 3.402823E+38
Min Layer Thickness= 3.402823E+38
Max Layer Thickness= 3.402823E+38
Number of Layers= 5

--- BEAVCK1T2.f01 (steady flow) ---

Flow Title=Flow
Program Version=6.20
Number of Profiles= 1
Profile Names=P100yr
River Rch & RM=BEAVCK1T2,Main,5329
     462
Boundary for River Rch & Prof#=BEAVCK1T2,Main            , 1
Up Type= 0
Dn Type= 3
Dn Slope=0.01963
DSS Import GetInterval= 0
DSS Import GetPeak= 0
DSS Import FillOption= 0

--- BEAVCK1T2.g01 (geometry) ---

Geom Title=Geometry
Program Version=6.20

River Reach=BEAVCK1T2       ,Main
Reach XY= 30
2280010.21181305681485.1914392242280147.03408653681477.856604444
     2280279.419      681375.962     2280291.827      681321.334
     2280344.257      681274.863     2280441.742      681105.077
     2280578.178      681115.087     2280576.095      681027.587
     2280639.984      680894.948     2280802.484      680876.198
     2281042.761      680651.198      2281156.65      680594.254
2281315.19163784 680551.57339763     2281324.011      680488.004
     2281473.317      680376.893     2281766.372      680335.921
2281956.24477705680164.162633054       2282025.4      680029.671
     2282133.039      680015.782     2282221.747      679952.853
      2282294.15      679944.254     2282307.393      679880.903
 2282734.9858238679612.049671893      2282969.15      679390.087
2283105.59326756679338.9855230192283307.06056132679408.400854282
     2283834.037      679111.0942283885.81841022678989.956358989
     2283814.593      678820.816     2283837.272      678766.005

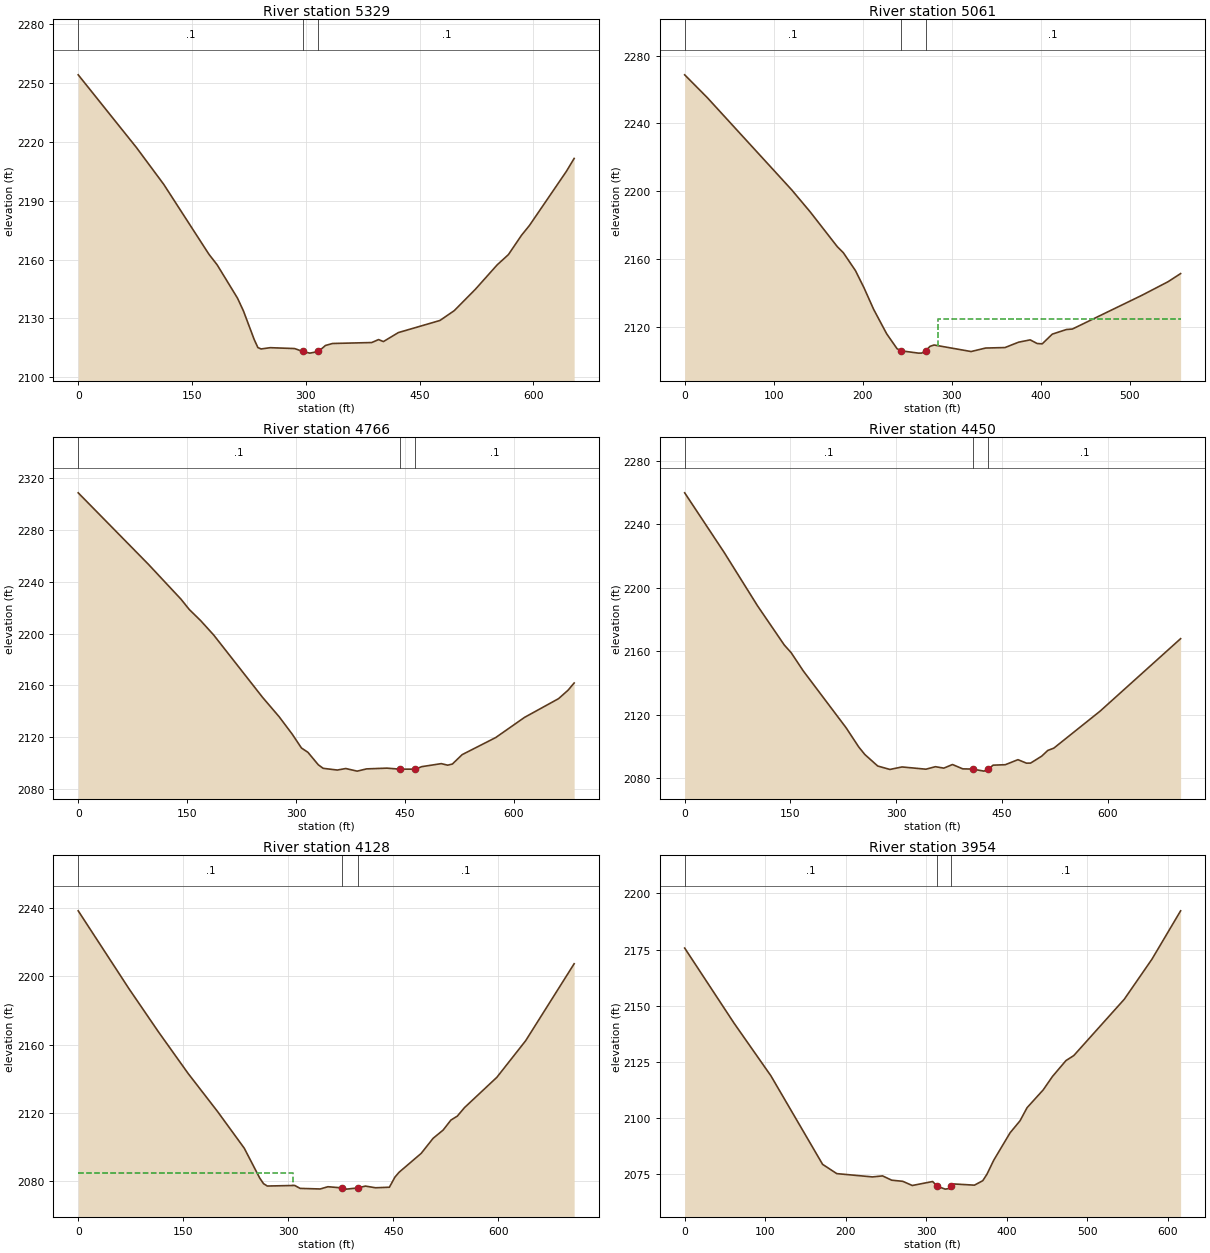
Type RM Length L Ch R = 1 ,5329    ,273.1,267.6,259
XS GIS Cut Line= 4
 2280163.4829426681729.5000737952280004.93187459 681552.83143576
2280014.04285726681467.131478504 2279838.6393864681187.203215921
#Sta/Elev= 30
       0 2254.08    76.8 2217.04   112.8 2198.29   172.4 2162.68   183.2 2157.32
     210 2140.37   217.8  2133.9     232 2119.32   236.9 2115.19   241.1 2114.47
   253.1 2115.12   285.3 2114.68  296.15 2113.19   305.4 2112.35  316.812113.189
   325.9 2116.23   335.3 2117.26     387 2117.74     396 2119.25   402.4 2118.23
   422.1 2122.81   476.9 2128.97   495.8 2133.98   523.7 2144.88   552.4  2157.3
   567.2 2162.51   584.6 2172.43   594.9 2177.33   643.5 2204.83   653.9 2211.49
#Mann= 3 ,-1,0
       0      .1       0  296.15    .045       0  316.81      .1       0
Bank Sta=296.15,316.81
XS Rating Curve= 0 ,0
Exp/Cntr=0.3,0.1

Type RM Length L Ch R = 1 ,5061    ,298.7,295.3,286.5
XS GIS Cut Line= 4
2280373.02472784681614.9364410752280254.45203721681412.939240113
2280199.16472682681317.7222055552280048.66038187681167.217860608
#Sta/Elev= 30
       0 2268.72    25.3 2255.31   120.2 2200.83   141.2 2187.69   171.4 2167.31
   178.3 2163.66   191.9 2153.11   201.5 2142.96   212.3 2130.27   226.9 2115.86
   238.6 2107.03   243.2 2105.77   262.7 2104.41   266.3 2104.43  270.782105.754
   275.6  2108.4   280.2 2109.21   321.8 2105.35   338.1 2107.41   359.9  2107.7
   375.1 2110.86   388.2 2112.23     396 2110.09   401.7 2109.89     413 2115.62
   428.9 2118.35   435.6 2118.63   513.7 2138.55   543.1 2146.57   557.2 2151.37
#Mann= 3 ,-1,0
       0      .1       0   243.2    .045       0  270.78      .1       0
#XS Ineff= 2 , 0
                          284.85         2124.75
Permanent Ineff=
       F       F
Bank Sta=243.2,270.78
XS Rating Curve= 0 ,0
Exp/Cntr(USF)=0,0
Exp/Cntr=0.3,0.1

Type RM Length L Ch R = 1 ,4766    ,317.2,316.3,311.4
XS GIS Cut Line= 4
2280644.33311444681527.216428621     2280491.724681231.047494345
2280373.25739708 681145.692829022280209.22754054681024.415300476
#Sta/Elev= 30
       0 2308.35    96.8 2253.24   141.8  2226.3   152.9 2218.55   168.8 2209.85
   186.8 2198.73     254  2150.8   276.8 2135.89   294.8  2122.5   307.5 2111.83
   316.4 2108.53   330.8 2098.84   337.5 2096.15   356.9 2094.83   368.6    2096
   384.3    2094   397.2 2095.72   425.3  2096.3   443.1 2095.52  464.472095.513
   473.2 2097.44   500.2 2099.77   508.9 2098.58   515.4 2099.44   528.9 2106.69
   575.1 2119.85   614.8 2135.38   661.7 2149.81   674.8 2156.32   683.2 2161.88
#Mann= 3 ,-1,0
       0      .1       0   443.1    .045       0  464.47      .1       0
Bank Sta=443.1,464.47
XS Rating Curve= 0 ,0
Exp/Cntr=0.3,0.1

Type RM Length L Ch R = 1 ,4450    ,313.5,321.8,324.2
XS GIS Cut Line= 4
2280826.75745777681324.1345930762280720.83875977681076.974598493
2280513.37393578 680993.926130722280317.13811187680915.431801156
#Sta/Elev= 30
       0 2259.73      56 2222.21   103.3 2188.61   141.3  2163.9   151.2 2158.96
   168.2 2147.61   229.2 2111.65   246.9  2099.7   255.6 2094.92   273.9 2087.65
   291.2 2085.49   308.4 2087.06   342.3 2085.65   355.8 2087.22   367.7 2086.32
     380 2088.59   394.6 2085.86  408.552085.717   424.7 2084.43     4312085.722
   437.6 2088.19   454.9 2088.47   472.9 2091.64     485 2089.45   490.8 2089.49
   506.6 2093.86   515.2 2097.45   523.8 2098.92   589.3 2122.15   703.7 2167.87
#Mann= 3 ,-1,0
       0      .1       0  408.55    .045       0     431      .1       0
Bank Sta=408.55,431
XS Rating Curve= 0 ,0
Exp/Cntr(USF)=0,0
Exp/Cntr=0.3,0.1

Type RM Length L Ch R = 1 ,4128    ,172.8,173.5,174
XS GIS Cut Line= 4
2280982.97582414681205.6655635612280900.83042744680964.626847632
2280756.22078289680804.7453700632280606.89576907680619.149533913
#Sta/Elev= 30
       0 2238.18    72.4 2192.72   114.6 2167.45     157 2143.12   199.1 2120.84
   237.2 2099.42   259.3 2081.97   264.7  2078.7   270.1 2077.32   309.3 2077.65
     317 2075.94   345.6  2075.6   356.7 2076.91   377.5 2076.21   383.4 2075.51
   399.5 2076.22   410.3 2077.29   424.6 2076.31   444.5 2076.62   452.4 2082.54
   458.4  2085.4   489.9  2096.4   506.9  2105.2   521.2 2110.01   532.5 2115.92
   541.5 2118.18   551.8 2123.17     598 2140.87   639.1 2162.24   708.4 2207.24
#Mann= 3 ,-1,0
       0      .1       0   377.5    .045       0   399.5      .1       0
#XS Ineff= 2 , 0
          307.46 2084.66
Permanent Ineff=
       F       F
Bank Sta=377.5,399.5
XS Rating Curve= 0 ,0
Exp/Cntr=0.3,0.1

Type RM Length L Ch R = 1 ,3954    ,231.9,234.8,236.2
XS GIS Cut Line= 4
2281085.69609254681039.985567396 2281036.5694791680870.932221151
2280899.30394155680704.7686756972280772.15270677680519.821425105
#Sta/Elev= 30
       0 2175.65    61.2 2142.22   107.1 2118.67   171.3 2079.19   188.9 2075.05
   233.2 2073.58   245.8 2074.03   257.1 2072.12   270.9 2071.61   282.7 2069.75
     308 2071.53  313.672069.418   323.6 2068.13   328.2 2068.37   331.22069.417
     334 2070.44   359.9  2069.9   370.3 2071.91   375.5 2074.81   383.9 2081.04
   404.2 2093.26   416.5 2098.59   425.3 2104.46   445.3 2112.39   456.8 2118.37
   473.6 2125.47   483.3  2127.7     546 2152.81   580.4 2170.69     616 2192.26
#Mann= 3 ,-1,0
       0      .1       0  313.67    .045       0   331.2      .1       0
Bank Sta=313.67,331.2
XS Rating Curve= 0 ,0
Exp/Cntr(USF)=0,0
Exp/Cntr=0.3,0.1

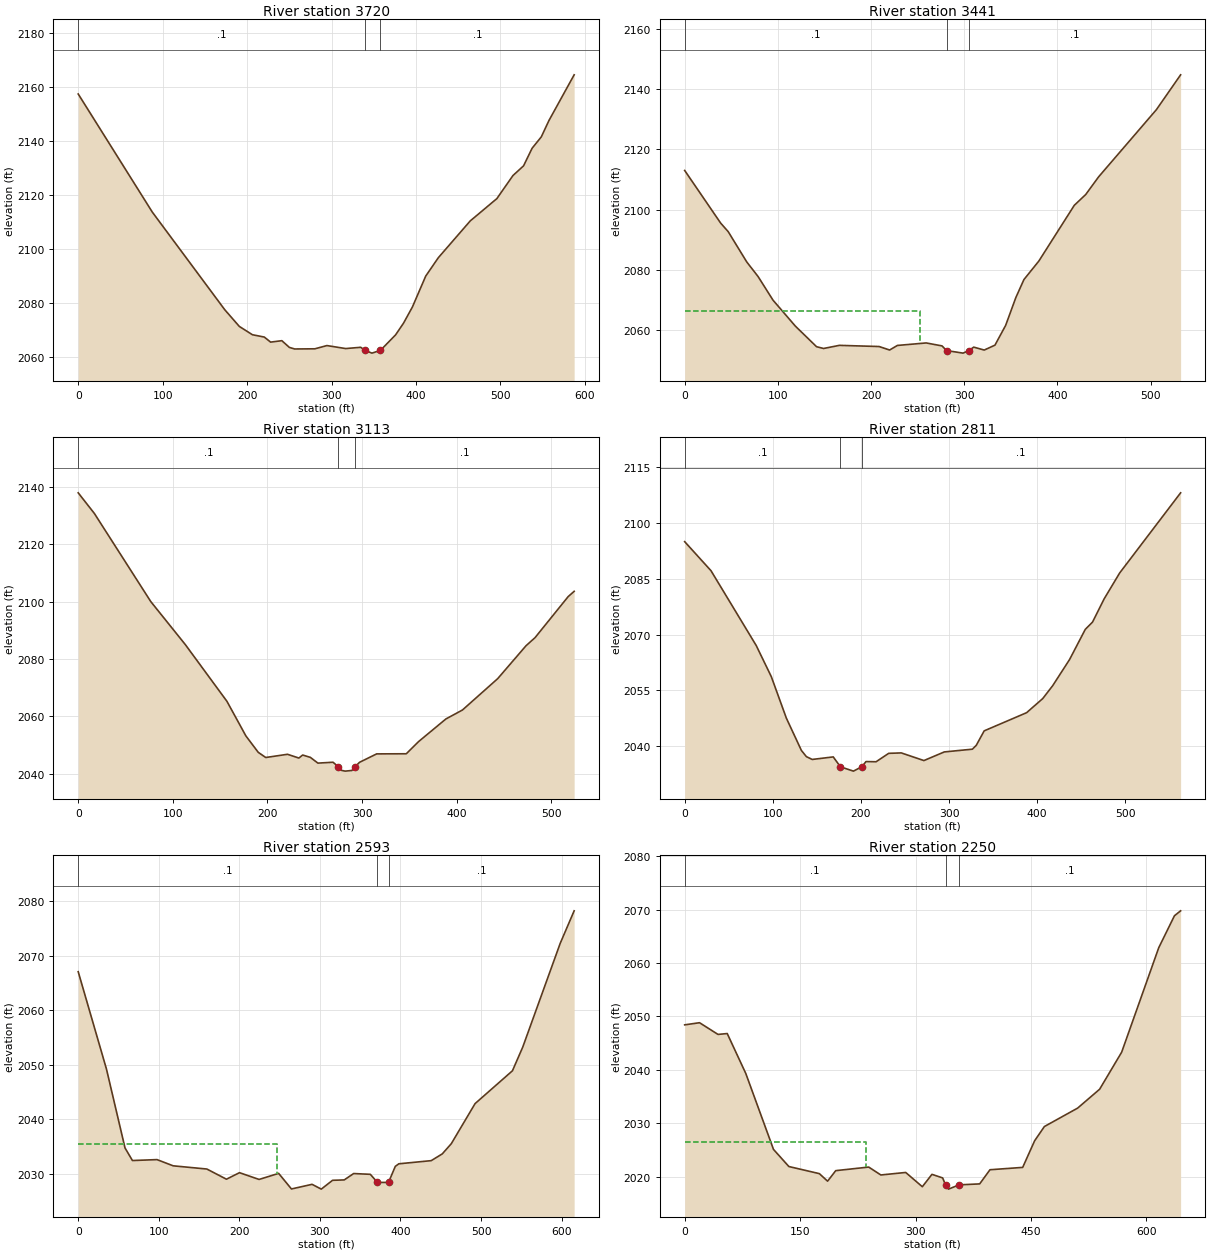
Type RM Length L Ch R = 1 ,3720    ,279.3,278.3,271.3
XS GIS Cut Line= 4
2281224.47516364680943.0485818182281180.27269891680733.907315763
2281110.51987733 680589.919793112280971.53799605680427.665469564
#Sta/Elev= 30
       0 2157.31    87.8 2113.54   173.6 2077.38   190.8 2071.21   206.3 2068.13
   220.4 2067.26   227.9 2065.39   241.2 2065.92   250.1 2063.43   256.3 2062.85
   280.3 2062.91   294.6 2064.11   316.8    2063   334.6 2063.47  339.932062.308
   347.9 2061.31  357.892062.309   375.9 2068.07   385.3 2072.41   395.8 2078.38
   411.6 2089.85   426.5 2096.65   464.3 2110.28   495.9 2118.57   514.9 2127.09
   527.5  2130.7   537.6 2137.21   548.5 2141.43   557.5 2147.45   587.4 2164.41
#Mann= 3 ,-1,0
       0      .1       0  339.93    .045       0  357.89      .1       0
Bank Sta=339.93,357.89
XS Rating Curve= 0 ,0
Exp/Cntr=0.3,0.1

Type RM Length L Ch R = 1 ,3441    ,320.7,327.8,336.9
XS GIS Cut Line= 4
2281439.72430435680731.7446186462281430.36134979680583.107714987
2281281.72444613680434.4708113272281148.30234363680324.456095233
#Sta/Elev= 30
       0 2113.03    38.6 2095.56    46.7 2092.72    66.7 2082.62    78.7 2077.85
    94.8 2069.97   118.8 2061.35   141.5 2054.53     149 2053.94     166 2054.98
   208.6 2054.59   219.9 2053.43   228.2 2054.95   259.1 2055.78   276.1  2054.8
  280.992053.248   298.7  2052.4  304.88 2053.25   310.1 2054.39   321.4 2053.42
   332.9 2055.05   344.4 2061.62   355.3 2070.83     364 2076.82     380 2082.96
     418 2101.45   430.3 2105.05   444.1  2110.9   506.1  2133.2   532.1 2144.77
#Mann= 3 ,-1,0
       0      .1       0  280.99    .045       0  304.88      .1       0
#XS Ineff= 2 , 0
          252.28 2066.22
Permanent Ineff=
       F       F
Bank Sta=280.99,304.88
XS Rating Curve= 0 ,0
Exp/Cntr(USF)=0,0
Exp/Cntr=0.3,0.1

Type RM Length L Ch R = 1 ,3113    ,311.2,302.4,290.8
XS GIS Cut Line= 4
2281618.85031094680634.2989525712281613.07989204680438.858329691
 2281617.9061366680331.8607998832281448.57031884680189.137485871
#Sta/Elev= 30
       0 2137.82    17.1 2130.63    76.7 2099.97   113.2    2085   157.2 2065.25
   177.2 2053.22   190.3  2047.5   198.2 2045.71   221.2 2046.83   233.2 2045.52
   237.2 2046.57   245.3 2045.76   253.3 2043.76   269.3 2044.06  275.02 2042.45
   277.3 2041.31   282.1 2040.97   289.3  2041.2   292.52042.448   297.3 2044.04
   315.4 2046.97   346.7 2047.01   359.7 2051.25   388.6 2059.13   406.1 2062.25
   443.3 2073.15   473.2 2084.59   482.8 2087.43   517.8 2101.71   524.1 2103.54
#Mann= 3 ,-1,0
       0      .1       0  275.02    .045       0   292.5      .1       0
Bank Sta=275.02,292.5
XS Rating Curve= 0 ,0
Exp/Cntr=0.3,0.1

Type RM Length L Ch R = 1 ,2811    ,219.3,218,216.1
XS GIS Cut Line= 4
2281874.41981809 680397.184423122281921.82494325680271.341770459
2281798.48150536680178.6762444852281549.22479983680064.820174929
#Sta/Elev= 30
       0 2095.01    29.9 2087.19    81.2 2067.08    98.3 2058.72   115.4 2047.55
   132.5 2038.86   138.1 2037.21   144.7 2036.45   168.6 2037.13  176.762034.473
   191.5 2033.31  200.932034.474   205.8 2035.88   217.2 2035.83   231.5 2038.09
   245.8 2038.21   271.5 2036.15   294.6 2038.47   326.5 2039.21   330.9 2040.25
   339.9 2044.14     388 2049.02   406.3 2052.81   417.5 2056.24   436.8 2063.32
   454.6 2071.42   462.8 2073.37     476 2079.62   493.6 2086.58   562.8 2108.14
#Mann= 3 ,-1,0
       0      .1       0  176.76    .045       0  200.93      .1       0
Bank Sta=176.76,200.93
XS Rating Curve= 0 ,0
Exp/Cntr=0.3,0.1

Type RM Length L Ch R = 1 ,2593    ,341.2,343.1,343.1
XS GIS Cut Line= 5
2282227.06070407680351.6979679222282103.02600024680133.367576687
2282036.43369046680081.1586031232281947.75604913680038.974974466
 2281775.7848231679980.386847347
#Sta/Elev= 30
       0 2067.07    35.1 2049.18    58.1 2034.71    67.3  2032.4    97.8 2032.57
   117.9 2031.43   159.7 2030.84     184 2028.97   200.2 2030.17   224.5 2028.93
   248.8 2030.04   264.7 2027.18   290.3 2028.03   301.7 2027.15   315.7 2028.77
   330.2 2028.84   341.9 2030.01   362.6 2029.87371.47132028.381385.17132028.383
   393.6 2031.33     398  2031.8   438.2 2032.38   451.9 2033.62   463.1 2035.49
   492.6 2042.85     539 2048.88   551.8 2053.23   598.3 2072.28   615.6 2078.25
#Mann= 3 ,-1,0
       0      .1       0371.4713    .045       0385.1713      .1       0
#XS Ineff= 2 , 0
          247.16 2035.51
Permanent Ineff=
       F       F
Bank Sta=371.4713,385.1713
XS Rating Curve= 0 ,0
Exp/Cntr(USF)=0,0
Exp/Cntr=0.3,0.1

Type RM Length L Ch R = 1 ,2250    ,225,227.4,227.7
XS GIS Cut Line= 4
2282429.90628378680224.4437954662282438.09886902680062.932829286
2282223.92128344679873.3329994212282065.92142522679756.296067406
#Sta/Elev= 30
       0 2048.42    19.3 2048.82    43.3 2046.63    55.3 2046.79    79.4 2039.32
   115.4  2025.1   135.4 2021.89     175 2020.56   185.7 2019.15   196.3 2021.12
   239.1 2021.79   254.9 2020.31   287.2 2020.78   308.8 2018.11   321.3 2020.43
   335.2 2019.76  338.91 2018.46   342.8 2017.66   356.6 2018.46   383.3 2018.64
   396.7 2021.29   439.2 2021.73   454.7 2026.71   467.4 2029.38   510.6 2032.83
   539.2 2036.37   567.8  2043.3     616 2062.87   636.4 2068.85   644.4 2069.77
#Mann= 3 ,-1,0
       0      .1       0  338.91    .045       0   356.6      .1       0
#XS Ineff= 2 , 0
          236.02 2026.46
Permanent Ineff=
       F       F
Bank Sta=338.91,356.6
XS Rating Curve= 0 ,0
Exp/Cntr(USF)=0,0
Exp/Cntr=0.3,0.1

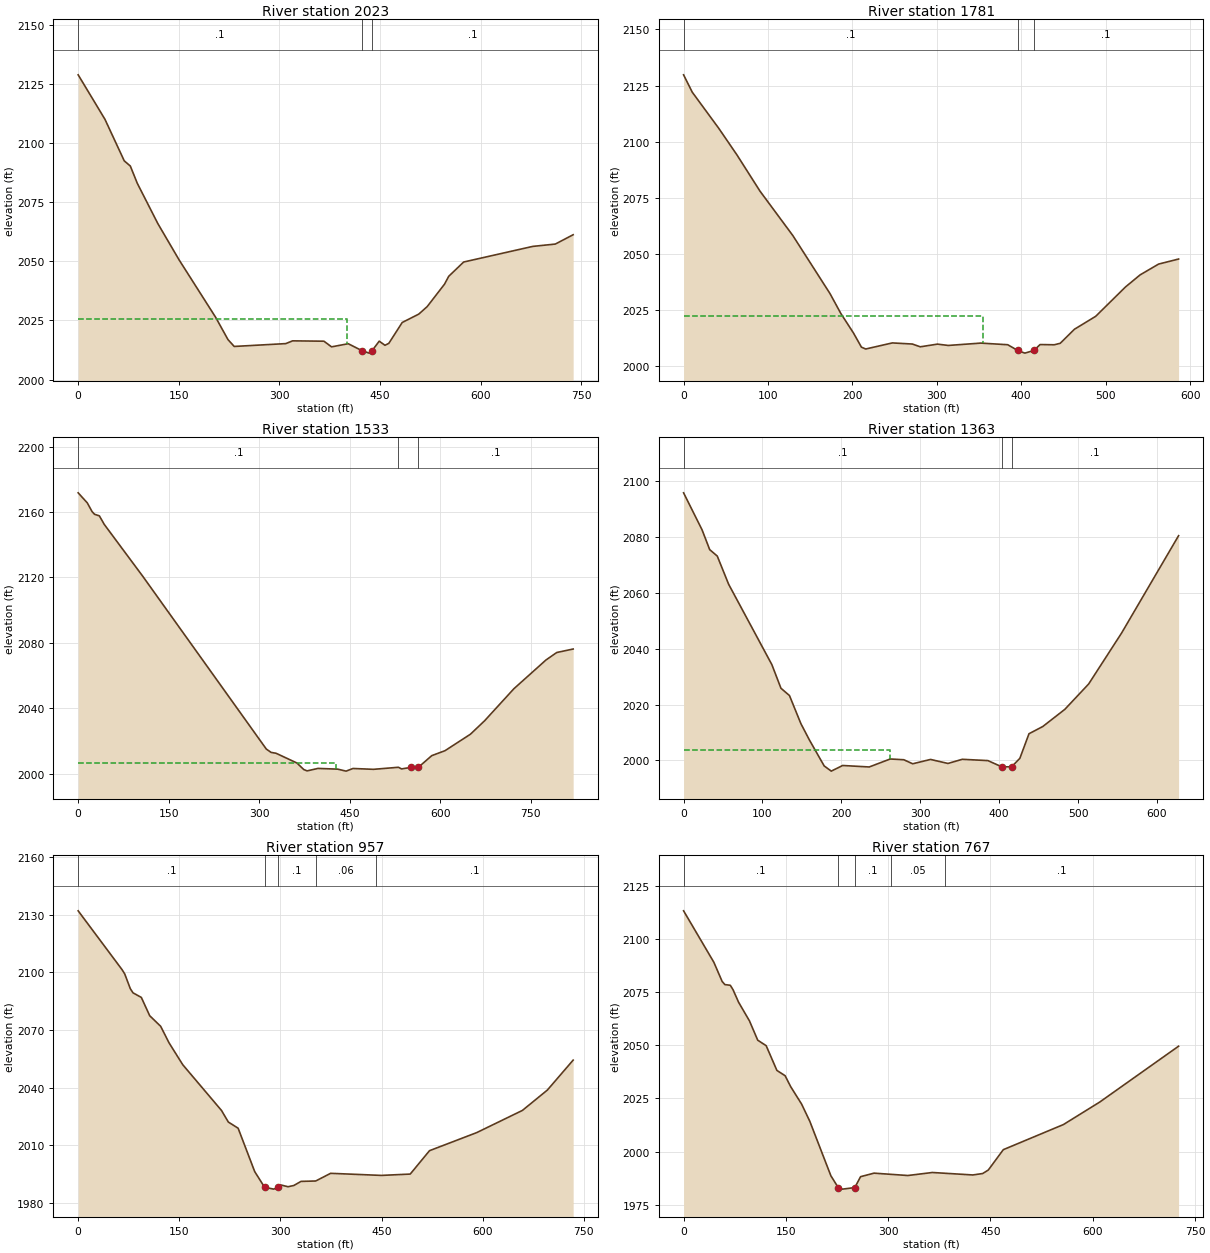
Type RM Length L Ch R = 1 ,2023    ,239.8,241.2,242
XS GIS Cut Line= 4
2282683.18166194680153.6303720872282570.31419603679945.037586648
2282436.39027851679782.1213919362282202.73517514679610.220631295
#Sta/Elev= 30
       0 2128.79    39.9 2110.02    68.7 2092.45    77.8 2090.24    88.1 2082.99
   118.8 2065.93   150.6 2050.54   205.2 2026.23   223.4 2016.89   232.7    2014
   309.5  2015.2   319.8 2016.37   366.5 2016.22   377.8 2013.83   402.7 2015.16
  423.062012.245   433.8 2011.18  438.332012.243   448.9 2016.23   457.5 2014.49
   463.2  2015.3   483.2 2024.13   507.9 2027.67   520.4 2030.83   546.2 2040.29
   552.6 2043.66   574.8 2049.68   677.8 2056.28   711.5 2057.27   738.1 2061.21
#Mann= 3 ,-1,0
       0      .1       0  423.06    .045       0  438.33      .1       0
#XS Ineff= 2 , 0
          400.13 2025.72
Permanent Ineff=
       F       F
Bank Sta=423.06,438.33
XS Rating Curve= 0 ,0
Exp/Cntr=0.3,0.1

Type RM Length L Ch R = 1 ,1781    ,250,248.3,246.4
XS GIS Cut Line= 4
2282838.28900509680014.5333317452282754.84167257 679834.76460417
2282622.94105019679625.3855327952282494.55153577679567.686325311
#Sta/Elev= 30
       0 2129.79    10.3 2122.04    41.8 2105.89    63.2 2094.12    90.5 2077.98
   129.4 2058.19   173.5 2032.29   186.3 2023.46   201.3 2014.74   210.7 2008.45
   215.8 2007.64   247.3 2010.35     271 2009.85   280.4 2008.62   300.8 2009.81
   313.5 2009.22   352.1 2010.27     384 2009.54  395.932006.972   404.3  2005.8
  414.992006.973   422.3 2009.62   439.1 2009.52   446.2 2010.18     463 2016.43
   488.2  2022.2   523.5 2035.28   540.8 2040.65   562.7 2045.47   586.4 2047.72
#Mann= 3 ,-1,0
       0      .1       0  395.93    .045       0  414.99      .1       0
#XS Ineff= 2 , 0
          354.33 2022.25
Permanent Ineff=
       F       F
Bank Sta=395.93,414.99
XS Rating Curve= 0 ,0
Exp/Cntr(USF)=0,0
Exp/Cntr=0.3,0.1

Type RM Length L Ch R = 1 ,1533    ,169.8,169.8,169.9
XS GIS Cut Line= 4
2283011.53107358680004.2610469062282986.01394232679656.340224267
2282817.29206297679488.9330595892282607.19680661679385.867462126
#Sta/Elev= 30
       0 2171.71    15.1 2165.58    23.1 2160.22    27.2  2158.6    35.2 2157.62
    43.2 2152.44   107.4 2120.55   311.9  2015.1   319.9 2013.05     328 2012.54
   362.7 2006.57     374 2002.58   379.6 2001.76   397.6 2003.27   430.3 2002.82
   444.2 2001.61   455.6 2003.23   489.6 2002.71  530.91 2003.96   536.2 2002.96
   552.1 2003.92  563.91 2003.92   586.2 2011.08   608.1 2014.09   650.2 2024.14
   673.9 2032.43   722.2 2051.91   775.5 2069.53   793.4 2074.11   820.6 2076.25
#Mann= 3 ,-1,0
       0      .1       0  530.91    .045       0  564.11      .1       0
#XS Ineff= 2 , 0
          426.77 2006.74
Permanent Ineff=
       F       F
Bank Sta=552.1,563.91
XS Rating Curve= 0 ,0
Exp/Cntr(USF)=0,0
Exp/Cntr=0.3,0.1

Type RM Length L Ch R = 1 ,1363    ,406.3,406.2,397.6
XS GIS Cut Line= 4
2283211.89047851679720.6826540072283057.40172825679490.119897937
2282953.23885876679384.786659124 2282781.1945687 679279.45342031
#Sta/Elev= 30
       0 2095.92    23.5  2082.6    33.1 2075.56    42.7 2073.25    57.1 2063.16
   111.9 2034.35   123.4 2025.89   134.2 2023.27   148.7 2013.19   159.7 2007.24
   178.2 1998.05   187.2 1996.19   201.6 1998.21   235.3 1997.68   261.9 2000.54
   279.1 2000.27   290.4 1998.82     313 2000.38   335.1 1998.94   353.2 2000.43
   385.7 1999.96   403.5 1997.71   415.8 1997.75   426.2 2000.77   437.8 2009.59
   455.3 2012.18   483.2 2018.32   513.4 2027.41   555.2 2045.69   627.4 2080.56
#Mann= 3 ,-1,0
       0      .1       0   403.5    .045       0   415.8      .1       0
#XS Ineff= 2 , 0
          261.33 2003.67
Permanent Ineff=
       F       F
Bank Sta=403.5,415.8
XS Rating Curve= 0 ,0
Exp/Cntr(USF)=0,0
Exp/Cntr=0.3,0.1

Type RM Length L Ch R = 1 ,957     ,187.4,189.8,190.8
XS GIS Cut Line= 4
2283407.83811613679656.5335773092283349.45913054679400.636692237
2283161.93311433 679245.438405352282956.39097893679145.803901267
#Sta/Elev= 30
       0 2132.13      65 2101.52    69.1 2099.22    77.3 2091.58    81.4 2089.36
    93.7 2086.99   106.1 2077.46   122.4 2071.92   134.7 2063.38   155.2 2051.88
   212.7 2028.02   222.8    2022   237.3  2018.8   261.9 1996.18  276.571988.005
   290.1 1987.04  296.381988.006   300.5 1989.22   311.3 1988.29   319.8 1988.92
   330.6 1991.07   352.4 1991.28   374.5 1995.28   449.8 1994.19   492.6 1994.89
   521.2 2007.08   591.2  2016.5     659 2028.07     696 2038.67   734.3  2054.3
#Mann= 5 ,-1,0
       0      .1       0  276.57    .045       0  296.38      .1       0
  352.47     .06       0  442.47      .1       0
Bank Sta=276.57,296.38
XS Rating Curve= 0 ,0
Exp/Cntr(USF)=0,0
Exp/Cntr=0.3,0.1

Type RM Length L Ch R = 1 ,767     ,175.7,175.7,178
XS GIS Cut Line= 4
2283531.74219238679529.3967502492283511.84591394679316.389533982
2283374.91270348679137.323027999 2283115.0907144679016.774988023
#Sta/Elev= 30
       0 2113.19    44.4 2088.99    56.5    2080    60.5 2078.51    68.5 2078.18
    72.5 2076.11    80.6 2070.24    96.6 2061.44   108.7 2052.37   121.1 2049.78
   136.8 2038.16   148.9 2035.65   156.9 2030.59     173 2022.35     185 2014.29
     216 1988.59  226.771983.066   233.1 1982.34  251.041983.069   259.5 1988.19
   279.2 1989.85   328.8 1988.74   364.8 1990.16   424.1    1989   438.6 1989.68
   446.8 1991.32   468.8 2000.89     557 2012.71   610.2 2023.28   725.8 2049.54
#Mann= 5 ,-1,0
       0      .1       0  226.77    .045       0  251.04      .1       0
  303.93     .05       0  383.93      .1       0
Bank Sta=226.77,251.04
XS Rating Curve= 0 ,0
Exp/Cntr(USF)=0,0
Exp/Cntr=0.3,0.1

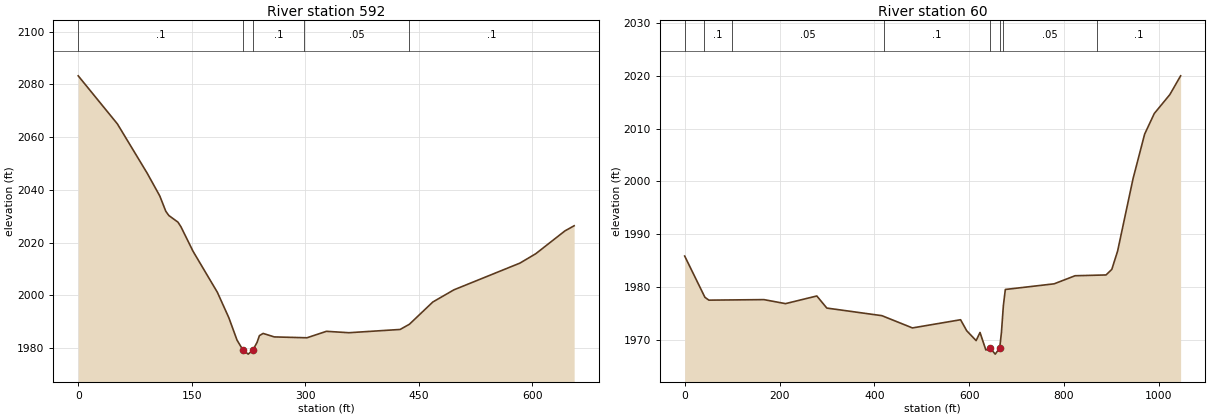
Type RM Length L Ch R = 1 ,592     ,542.8,532.1,523.7
XS GIS Cut Line= 4
2283660.22353949679432.9278085242283667.43328856679234.045785249
2283533.78806226679048.5157823962283320.71975981678967.759041819
#Sta/Elev= 30
       0 2083.25    51.8 2065.01    91.2  2046.3   107.8  2037.7   115.8 2031.86
   119.8 2030.26   131.8 2027.76   135.8 2025.99   151.8 2016.69   183.9 2001.16
     199 1991.56   209.9 1983.02  217.831979.196   224.7 1977.69  230.811979.193
   236.4 1982.15   239.5  1984.7   244.4 1985.54   259.2 1984.22   302.3 1983.89
   328.1 1986.34   357.8 1985.81   425.5 1987.05   437.7 1989.01   468.7 1997.46
   496.6 2002.08   583.8 2012.21   604.8 2015.78   643.3 2024.43   655.5 2026.38
#Mann= 5 ,-1,0
       0      .1       0  217.83    .045       0  230.81      .1       0
  299.01     .05       0  437.67      .1       0
Bank Sta=217.83,230.81
XS Rating Curve= 0 ,0
Exp/Cntr(USF)=0,0
Exp/Cntr=0.3,0.1

Type RM Length L Ch R = 1 ,60      ,,,
XS GIS Cut Line= 4
2284113.51194493679242.4114892612283987.11205835678778.945238495
2283734.31228521678836.8785198412283433.75863492678895.828266943
#Sta/Elev= 30
       0 1985.88    42.7 1978.07      51 1977.53   167.1 1977.63   212.7 1976.87
   278.7 1978.32   299.8 1976.03     416 1974.59   480.4 1972.27   581.9 1973.82
   594.9 1971.73   614.7 1969.87   622.9 1971.41   635.2  1968.1  644.551968.415
     655 1967.31  664.371968.432   668.1 1971.42   672.2 1976.53   676.3 1979.55
   779.3 1980.62   823.4 1982.15   888.7  1982.3   900.9 1983.36   913.1 1986.82
   945.7 2000.54   970.1 2008.96   990.5 2012.87  1023.2 2016.44    1046    2020
#Mann= 8 ,-1,0
       0     .05       0      40      .1       0     100     .05       0
     420      .1       0  644.55    .045       0  664.37      .1       0
  670.39     .05       0  869.75      .1       0
Bank Sta=644.55,664.37
XS Rating Curve= 0 ,0
Exp/Cntr(USF)=0,0
Exp/Cntr=0.3,0.1
LCMann Table=0

Chan Stop Cuts=-1
Use User Specified Reach Order=0
Composite Channel Slope=5